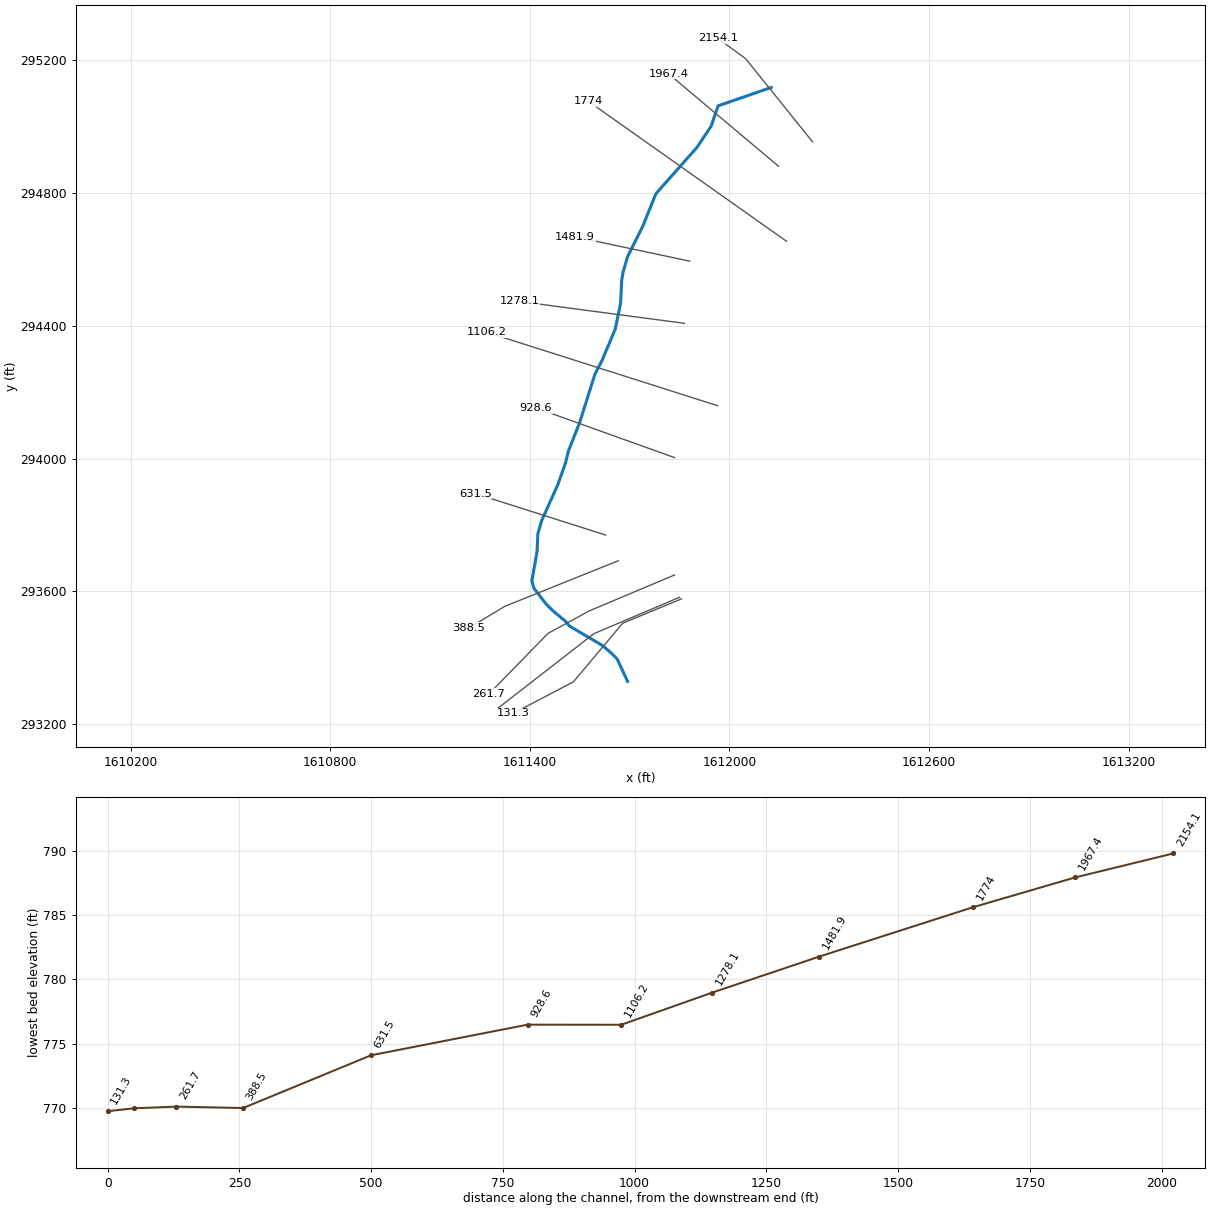
--- ROCKRN.prj (project) ---

Proj Title=ROCKRN
Current Plan=p01
Default Exp/Contr=0,0
English Units
Geom File=g01
Flow File=f01
Plan File=p01
BEGIN DESCRIPTION:
END DESCRIPTION:
DSS Export Rating Curves= 0
DSS Export Rating Curve Sorted= 0
DSS Export Volume Flow Curves= 0
DXF OffsetX= 0
DXF OffsetY= 0
DXF ScaleX= 0
DXF ScaleY= 0

--- ROCKRN.p01 (plan) ---

Plan Title=Floodplain
Program Version=4.00
Geom File=g01
Flow File=f01
K Sum by GR=0
Std Step Tol=0.01
Critical Tol=0.01
Num of Std Step Trials=20
Max Error Tol=0.3
Flow Tol Ratio=0.001
Split Flow NTrial=30
Split Flow Tol=0.02
Split Flow Ratio=0.02
Log Output Level=0
Friction Slope Method=1
Unsteady Friction Slope Method=2
Unsteady Bridges Friction Slope Method=1
Global Log Level=0
CheckData=False
Run HTab=0
Run UNet=0
Run PostProcess=0
UNET Theta=0
UNET Theta Warmup=0
UNET ZTol=0
UNET ZSATol=0
UNET MxIter=0
UNET MaxInSteps=0
UNET DtIC=0
UNET DtMin=0
UNET MaxCRTS=0
UNET WFStab=0
UNET SFStab=0
UNET WFX=0
UNET SFX=0
UNET DSS MLevel=0
UNET DZMax Abort=0
UNET Convert EG Bridges=0
UNET Use Existing IB Tables=0
UNET Froude Limit=0
UNET Froude Power=0
Write IC File=0
Echo Input=False
Echo Output=False
Write Detailed=0

--- ROCKRN.f01 (steady flow) ---

Flow Title=NFF Regression Equation
Program Version=4.10
Number of Profiles= 1
Profile Names=P100yr
River Rch & RM=ROCKRN,Main            ,2154.1
895.2671
River Rch & RM=ROCKRN,Main            ,631.5
919.5806
River Rch & RM=ROCKRN,Main            ,261.7
 920.297
Boundary for River Rch & Prof#=ROCKRN,Main            , 1
Up Type= 0
Dn Type= 3
Dn Slope=0.00529
DSS Import GetInterval= 0
DSS Import GetPeak= 0
DSS Import FillOption= 0

--- ROCKRN.g01 (geometry) ---

Geom Title=USGS 10m DEM
Program Version=4.10

River Reach=ROCKRN          ,Main
Reach XY= 30
     1612125.371      295117.937     1611965.663      295062.506
     1611945.047      295001.742     1611901.644      294936.638
      1611778.98       294798.08     1611738.667      294698.255
     1611693.609      294608.138     1611680.217      294561.938
     1611675.761      294534.463     1611672.791      294468.373
     1611656.454      294389.659     1611617.098      294296.093
     1611595.562      294254.509     1611550.265      294110.448
     1611515.363      294021.338     1611507.938      293989.407
     1611484.175      293921.832     1611435.164      293812.672
     1611424.026      293773.315     1611421.798      293721.334
     1611406.204      293632.224     1611412.144      293609.947
     1611449.274      293561.679     1611467.096      293543.857
      1611508.68      293508.956     1611518.334      293496.332
      1611617.84      293437.668     1611643.088      293416.133
     1611662.395      293396.826     1611693.801      293329.012

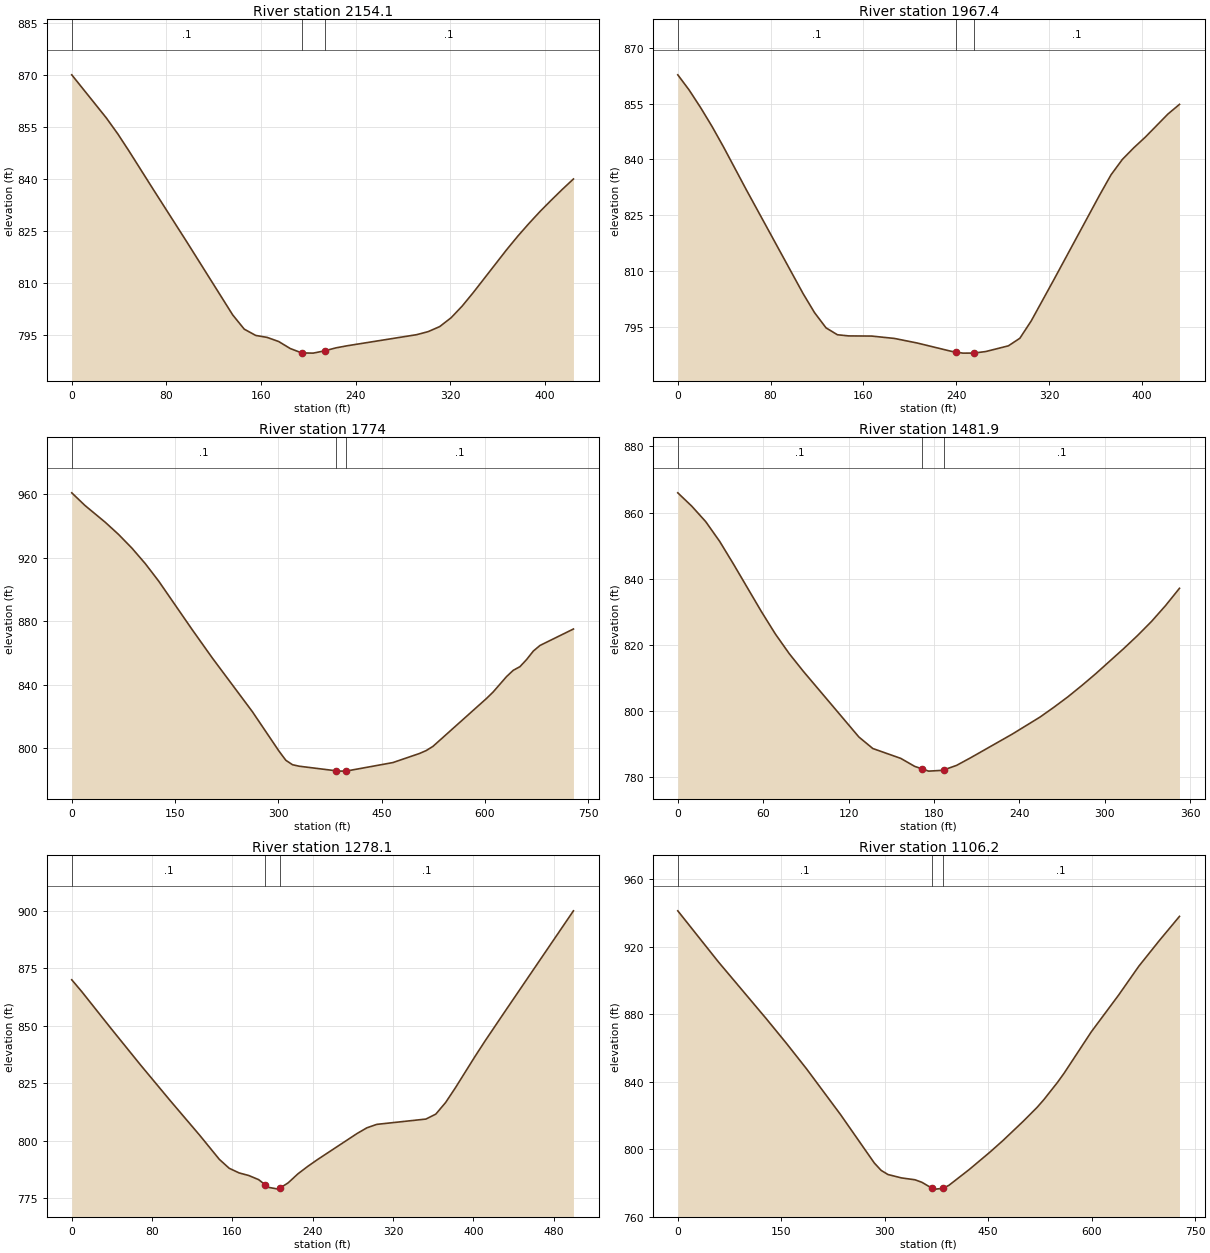
Type RM Length L Ch R = 1 ,2154.1  ,181.5,186.7,191.7
XS GIS Cut Line= 3
     1612249.035      294954.903     1612048.198      295204.952
     1611964.675      295265.846
#Sta/Elev= 30
       0     870    29.2  857.59    38.9  852.99    48.6  847.93      68  837.46
    97.2  821.88   136.1  800.78   145.8   796.7   155.5  794.88   165.2  794.31
   174.9  793.13   184.7  791.11   194.4  789.84   204.1  789.78   214.1  790.47
   223.5  791.31   233.2  791.92   291.6   795.1   301.3  795.98     311  797.42
   320.7  799.98   330.1  803.36   339.5  807.27   367.7  819.62   377.1  823.51
   386.5  827.16   395.9  830.62   405.3  833.85   414.7  836.98   424.1  839.98
#Mann= 3 , 0 , 0
       0      .1       0   194.4    .045       0   214.1      .1       0
Bank Sta=194.4,214.1
XS Rating Curve= 0 ,0
Exp/Cntr=0.3,0.1

Type RM Length L Ch R = 1 ,1967.4  ,191.1,193.4,195.7
XS GIS Cut Line= 2
     1612147.304      294880.648     1611816.575      295159.294
#Sta/Elev= 30
       0  862.77     9.8  858.68    19.7  853.94    29.5   848.9    39.3  843.44
      59   831.9   108.1  803.88   117.9   798.8   127.8  794.71   137.6  792.85
   147.4  792.54   167.1   792.5   186.8  791.86   206.4  790.63   235.9  788.39
     240  788.19   245.7  787.91     255  787.92   265.4  788.33     285  789.87
   294.9  791.91   304.7  796.58   324.4  807.77   363.7  830.45   373.5  835.88
   383.3  840.03   393.2  843.17     403     846   422.6  852.24   432.5  854.82
#Mann= 3 , 0 , 0
       0      .1       0     240    .045       0     255      .1       0
Bank Sta=240,255
XS Rating Curve= 0 ,0
Exp/Cntr=0.3,0.1

Type RM Length L Ch R = 1 ,1774    ,282.8,292.1,301.5
XS GIS Cut Line= 2
     1612171.682       294654.53       1611576.8      295075.628
#Sta/Elev= 30
       0   960.7    19.4  952.67    48.6   942.2      68  934.52    87.5  925.86
   106.9  916.11   126.3  905.15   174.9  874.66   204.1  856.85   262.4     823
   301.2  798.11     311  792.42   320.7  789.63   330.4  788.69     384  785.81
   388.7   785.6     399  785.66   466.5  790.98   505.3  796.72     515  798.56
   524.8   801.2   602.5  831.31   612.2   835.4   631.7  845.11   641.4  849.04
   651.1  851.32   660.8  855.83   670.5  861.13   680.2  864.66   728.8  875.02
#Mann= 3 , 0 , 0
       0      .1       0     384    .045       0     399      .1       0
Bank Sta=384,399
XS Rating Curve= 0 ,0
Exp/Cntr=0.3,0.1

Type RM Length L Ch R = 1 ,1481.9  ,202.2,203.8,205.5
XS GIS Cut Line= 2
      1611880.82      294594.779     1611536.127      294667.927
#Sta/Elev= 30
       0  865.97     9.8  861.94    19.6  857.26    29.4  851.29    39.2  844.35
    58.7  830.06    68.5  823.28    78.3   817.3    88.1  812.01   127.2  792.09
     137   788.6   156.6  785.62   166.4   783.2   171.7  782.42   176.2  781.76
     186     782   186.7  782.11   195.8  783.49   205.6  785.78   234.9  792.95
   254.5  798.13   264.3  801.12   274.1  804.27   283.8  807.66   293.6  811.24
   313.2  818.83     323  822.81   332.8  827.07   342.6  831.84   352.4  837.08
#Mann= 3 , 0 , 0
       0      .1       0   171.7    .045       0   186.7      .1       0
Bank Sta=171.7,186.7
XS Rating Curve= 0 ,0
Exp/Cntr=0.3,0.1

Type RM Length L Ch R = 1 ,1278.1  ,175.8,171.9,167.9
XS GIS Cut Line= 2
     1611864.347      294407.653     1611369.047       294473.37
#Sta/Elev= 30
       0     870     9.8  864.95    39.2  848.78    68.6   832.9      98  817.47
   127.4  802.39     147  791.89   156.8  788.02   166.6  786.01   176.3  784.87
   186.1  783.08   192.3  780.96   195.9  779.73   205.7  778.95   207.3   779.4
   215.5  781.68   225.3  785.62   235.1  788.87   244.9  791.85   284.1  803.13
   293.9  805.61   303.7  807.11   352.7  809.42   362.5  811.56   372.3  816.61
   382.1  823.06   401.7  836.73   411.5  843.33   431.1  856.02   499.6  899.99
#Mann= 3 , 0 , 0
       0      .1       0   192.3    .045       0   207.3      .1       0
Bank Sta=192.3,207.3
XS Rating Curve= 0 ,0
Exp/Cntr=0.3,0.1

Type RM Length L Ch R = 1 ,1106.2  ,178.4,177.6,176.8
XS GIS Cut Line= 2
     1611964.478      294159.494     1611271.461      294380.376
#Sta/Elev= 30
       0  941.31      59     911   127.8  877.65   157.3  862.93   186.8  847.65
   235.9  820.66     285  791.91   294.9  787.54   304.7  785.12   324.4   783.1
     344  781.99   353.8  780.53   363.7  778.16   369.2  777.21   373.5  776.46
   384.2  776.89   393.2  778.74   422.7  788.12   452.2  798.24   471.8  805.37
   501.3  816.82     521  824.91   530.8  829.48   550.4  839.62   560.3  845.24
   599.6  869.66   638.9  891.25   668.4  908.47   697.9  923.55   727.4  938.02
#Mann= 3 , 0 , 0
       0      .1       0   369.2    .045       0   384.2      .1       0
Bank Sta=369.2,384.2
XS Rating Curve= 0 ,0
Exp/Cntr=0.3,0.1

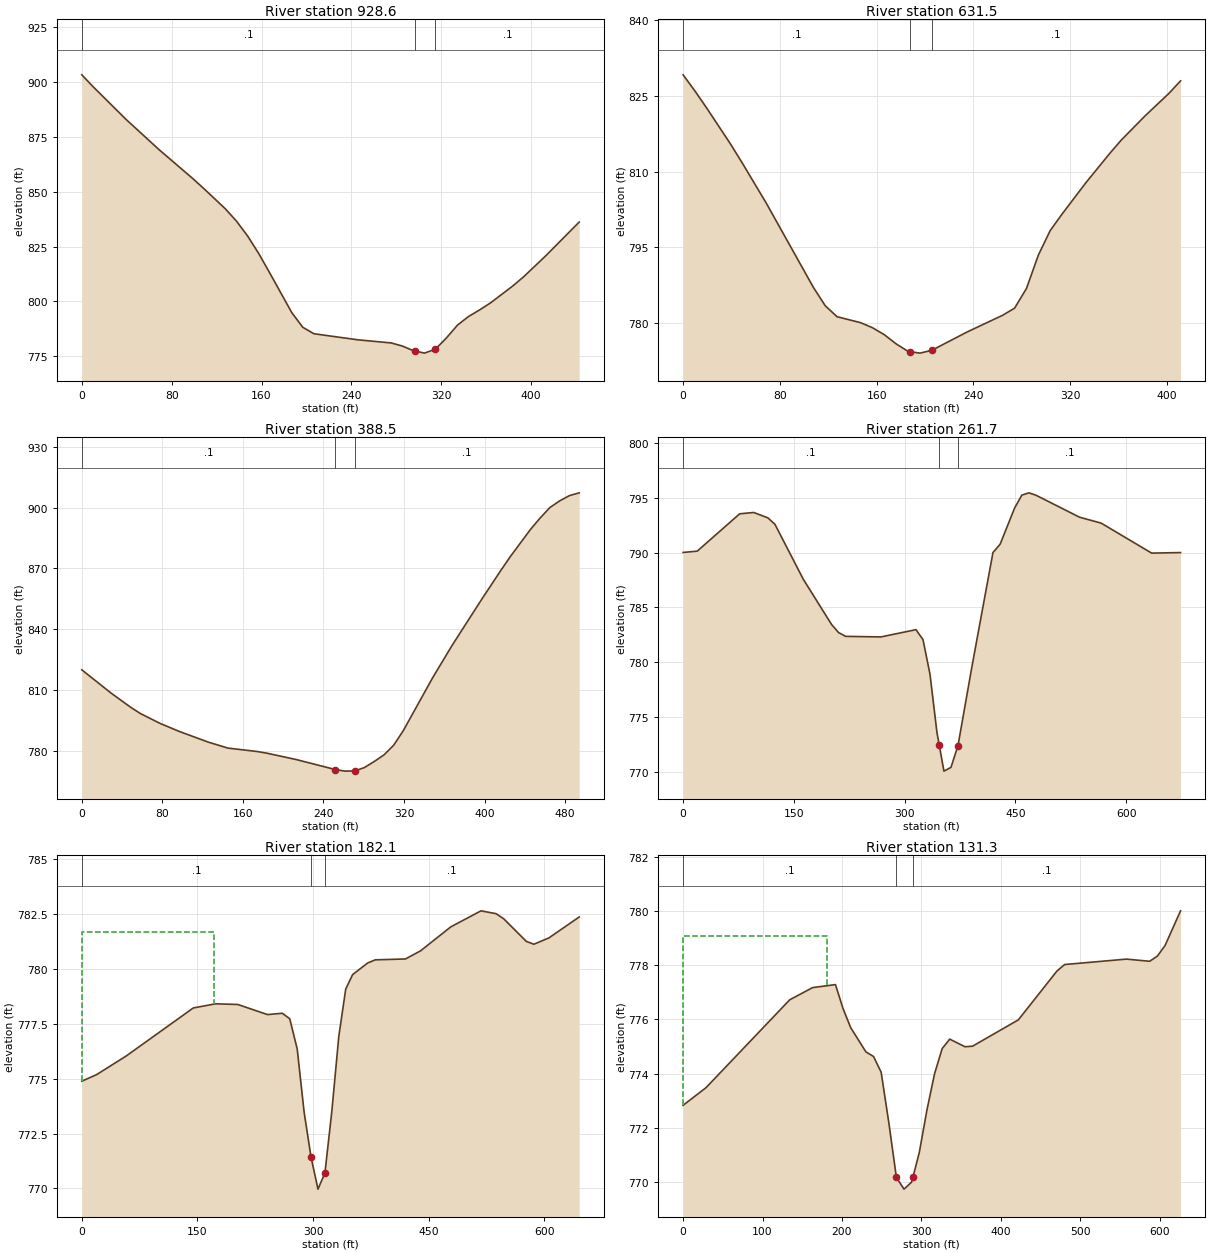
Type RM Length L Ch R = 1 ,928.6   ,296.1,297.1,297.8
XS GIS Cut Line= 2
     1611834.842      294003.256      1611418.19       294152.79
#Sta/Elev= 30
       0  903.23     9.8  897.96    39.4  882.93    68.9  869.09    98.4  856.16
   108.2  851.62   127.9  842.13   137.7  836.58   147.6  829.82   157.4  821.91
   167.2  813.07   186.9  794.92   196.7  788.24   206.6   785.3   245.9  782.52
   275.4  781.11   285.3   779.7   295.1  777.59   296.6  777.42     305  776.47
   314.8   778.3   324.6  783.43   334.5  789.29   344.3  793.18   354.1  796.16
     364  799.44   383.6  807.06   393.5  811.36   413.2  820.94   442.7  836.18
#Mann= 3 , 0 , 0
       0      .1       0   296.6    .045       0   314.8      .1       0
Bank Sta=296.6,314.8
XS Rating Curve= 0 ,0
Exp/Cntr=0.3,0.1

Type RM Length L Ch R = 1 ,631.5   ,227.5,242.9,258.9
XS GIS Cut Line= 2
     1611627.773      293769.971     1611235.846      293894.971
#Sta/Elev= 30
       0  829.18     9.8  825.97    19.6  822.57    39.2  815.48      49  811.69
    68.6  803.85   107.7  787.12   117.5  783.48   127.3   781.3   146.9  780.11
   156.7  779.11   166.5  777.72   176.3   775.9   186.1  774.43   187.4  774.38
   195.9  774.09   205.7  774.65   235.1   778.3   264.5  781.61   274.2  783.01
     284   786.9   293.8  793.49   303.6  798.35   313.4  801.61     333  807.79
   352.6  813.55   362.4  816.27     382  821.04   401.6  825.46   411.4  827.98
#Mann= 3 , 0 , 0
       0      .1       0   187.4    .045       0   205.7      .1       0
Bank Sta=187.4,205.7
XS Rating Curve= 0 ,0
Exp/Cntr=0.3,0.1

Type RM Length L Ch R = 1 ,388.5   ,123.8,126.8,129.3
XS GIS Cut Line= 3
     1611665.615      293692.534     1611324.387      293555.127
     1611216.314      293490.023
#Sta/Elev= 30
       0     820      29  808.54    48.4  801.56    58.1  798.45    77.4  793.62
    96.8  789.58   125.8  784.28   145.2  781.35   174.2  779.67   183.9  778.84
     213   775.7   251.7  770.78   261.4  769.99     271  770.08   280.7  771.75
   290.4  774.73   300.1  777.99   309.8   782.8   319.4  790.04   348.5  816.11
   367.8  832.05     397  854.65   416.4  869.22   426.1   876.2   445.5  889.19
   455.2   894.9   464.9  900.07   474.6  903.36   484.3  905.96     494  907.33
#Mann= 3 , 0 , 0
       0      .1       0   251.7    .045       0     271      .1       0
Bank Sta=251.7,271
XS Rating Curve= 0 ,0
Exp/Cntr=0.3,0.1

Type RM Length L Ch R = 1 ,261.7   ,78,79.5,83.1
XS GIS Cut Line= 4
     1611834.755      293649.724      1611579.08      293541.808
     1611454.342      293473.636     1611277.179      293291.478
#Sta/Elev= 30
       0  790.01    19.1  790.13    76.6  793.53    95.7  793.65   114.8  793.16
   124.4  792.57   162.7  787.58     201  783.46   210.5  782.72   220.1  782.37
     268  782.32   315.4  782.98   324.9  782.08   334.4  778.93   343.8  773.64
   346.8  772.52   353.3   770.1   362.8  770.44   372.3  772.41   391.2  779.61
   419.7     790   429.4  790.76     449  794.05   458.8  795.23   468.5  795.44
   478.3  795.21     537  793.22   566.3  792.68   634.7  789.95   673.8     790
#Mann= 3 , 0 , 0
       0      .1       0   346.8    .045       0   372.3      .1       0
Bank Sta=346.8,372.3
XS Rating Curve= 0 ,0
Exp/Cntr=0.3,0.1

Type RM Length L Ch R = 1 ,182.1   ,43.8,50.8,55.8
XS GIS Cut Line= 4
     1611849.412      293582.382     1611592.285        293472.9
     1611535.642      293428.619     1611303.622      293248.181
#Sta/Elev= 30
       0  774.88    19.3  775.18    57.8  776.03   144.6  778.21   173.5   778.4
   202.4  778.37   240.9  777.91   260.2  777.97   269.8  777.72   279.5  776.34
   288.4  773.48   297.4  771.43   306.4  769.97   315.4   770.7   324.4  773.51
   333.4  776.91   342.4  779.07   351.4  779.73     371  780.26   380.8   780.4
   419.9  780.44   439.5  780.81   478.7   781.9   517.9  782.63   537.5   782.5
   547.3  782.27   576.7  781.24   586.5  781.11   606.1   781.4   645.3  782.35
#Mann= 3 , 0 , 0
       0      .1       0   297.4    .045       0   315.4      .1       0
#XS Ineff= 2 , 0
          171.05  781.65
Permanent Ineff=
       F       F
Bank Sta=297.4,315.4
XS Rating Curve= 0 ,0
Exp/Cntr=0.3,0.1

Type RM Length L Ch R = 1 ,131.3   ,141.3,131.3,121.3
XS GIS Cut Line= 4
     1611855.828      293577.836     1611678.745      293504.224
     1611530.828      293327.836     1611350.005      293232.951
#Sta/Elev= 30
       0  772.83    28.8  773.48   134.2  776.72     163  777.17   191.8  777.28
   201.4  776.39     211  775.69   230.1   774.8   239.7  774.63   249.3  774.05
   258.9   772.2   268.5  770.17   278.1  769.74   287.7     770   289.4  770.19
   297.3  771.09   306.9  772.65   316.5  773.99   326.1  774.92   335.6  775.27
   354.8  774.99   364.4  775.01     422  775.98   470.6  777.78   480.3  778.02
   558.1  778.22   587.3  778.14     597  778.33   606.7  778.72   626.2     780
#Mann= 3 , 0 , 0
       0      .1       0   268.5    .045       0   289.4      .1       0
#XS Ineff= 2 , 0
          181.11  779.06
Permanent Ineff=
       F       F
Bank Sta=268.5,289.4
XS Rating Curve= 0 ,0
Exp/Cntr=0.3,0.1

Chan Stop Cuts=-1
Use User Specified Reach Order=0
Composite Channel Slope=5